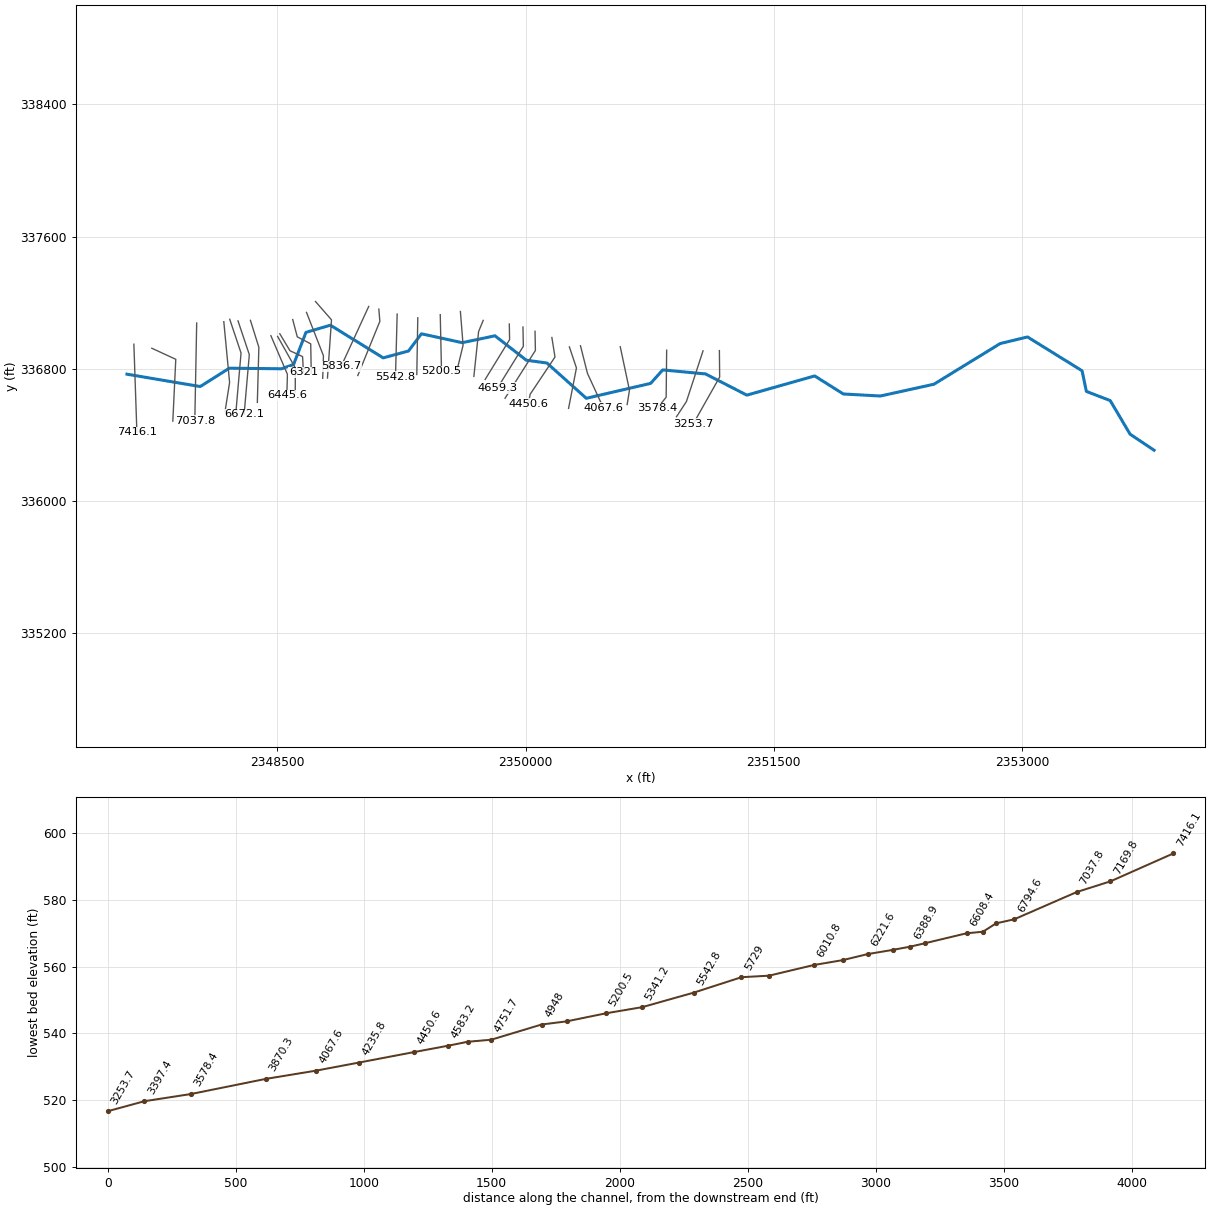
--- TUBRUN.prj (project) ---

Proj Title=TUBRUN
Current Plan=p01
Default Exp/Contr=0,0
English Units
Geom File=g01
Flow File=f01
Plan File=p01
BEGIN DESCRIPTION:
END DESCRIPTION:
DSS Export Rating Curves= 0
DSS Export Rating Curve Sorted= 0
DSS Export Volume Flow Curves= 0
DXF OffsetX= 0
DXF OffsetY= 0
DXF ScaleX= 0
DXF ScaleY= 0

--- TUBRUN.p01 (plan) ---

Plan Title=Floodplain
Program Version=4.00
Geom File=g01
Flow File=f01
K Sum by GR=0
Std Step Tol=0.01
Critical Tol=0.01
Num of Std Step Trials=20
Max Error Tol=0.3
Flow Tol Ratio=0.001
Split Flow NTrial=30
Split Flow Tol=0.02
Split Flow Ratio=0.02
Log Output Level=0
Friction Slope Method=1
Unsteady Friction Slope Method=2
Unsteady Bridges Friction Slope Method=1
Global Log Level=0
CheckData=False
Run HTab=0
Run UNet=0
Run PostProcess=0
UNET Theta=0
UNET Theta Warmup=0
UNET ZTol=0
UNET ZSATol=0
UNET MxIter=0
UNET MaxInSteps=0
UNET DtIC=0
UNET DtMin=0
UNET MaxCRTS=0
UNET WFStab=0
UNET SFStab=0
UNET WFX=0
UNET SFX=0
UNET DSS MLevel=0
UNET DZMax Abort=0
UNET Convert EG Bridges=0
UNET Use Existing IB Tables=0
UNET Froude Limit=0
UNET Froude Power=0
Write IC File=0
Echo Input=False
Echo Output=False
Write Detailed=0

--- TUBRUN.f01 (steady flow) ---

Flow Title=NFF Regression Equation
Program Version=4.00
Number of Profiles=1
Profile Names=P100yr
River Rch & RM=TUBRUN,Main      ,7416.1
524.7730
River Rch & RM=TUBRUN,Main      ,7169.8
525.3748
River Rch & RM=TUBRUN,Main      ,6794.6
616.6622
Boundary for River Rch & Prof#=TUBRUN,Main      ,1
Up Type=0
Dn Type=3
Dn Slope=0.011818

--- TUBRUN.g01 (geometry) ---

Geom Title=USGS 10m DEM
Program Version=4.10

River Reach=TUBRUN          ,Main
Reach XY= 30
     2347591.274      336766.206     2348033.982      336691.553
      2348209.33      336802.664     2348525.302      336799.192
     2348598.218      336825.234     2348672.871      337019.678
     2348820.441      337063.081     2349139.885      336865.164
     2349292.663      336906.831     2349370.788      337010.998
     2349617.316      336957.178     2349815.232      336998.845
     2350004.468      336851.275     2350129.469      336833.914
     2350367.316      336620.373     2350756.205       336710.65
     2350829.121      336792.248     2351087.802      336767.942
     2351337.802       336639.47     2351747.524      336755.789
     2351921.135      336646.414     2352145.093      336634.261
      2352468.01      336705.442     2352869.052       336951.97
     2353033.982        336991.9     2353363.843      336787.039
     2353389.885      336662.039     2353533.982      336606.484
     2353653.774      336403.359     2353798.967      336305.883

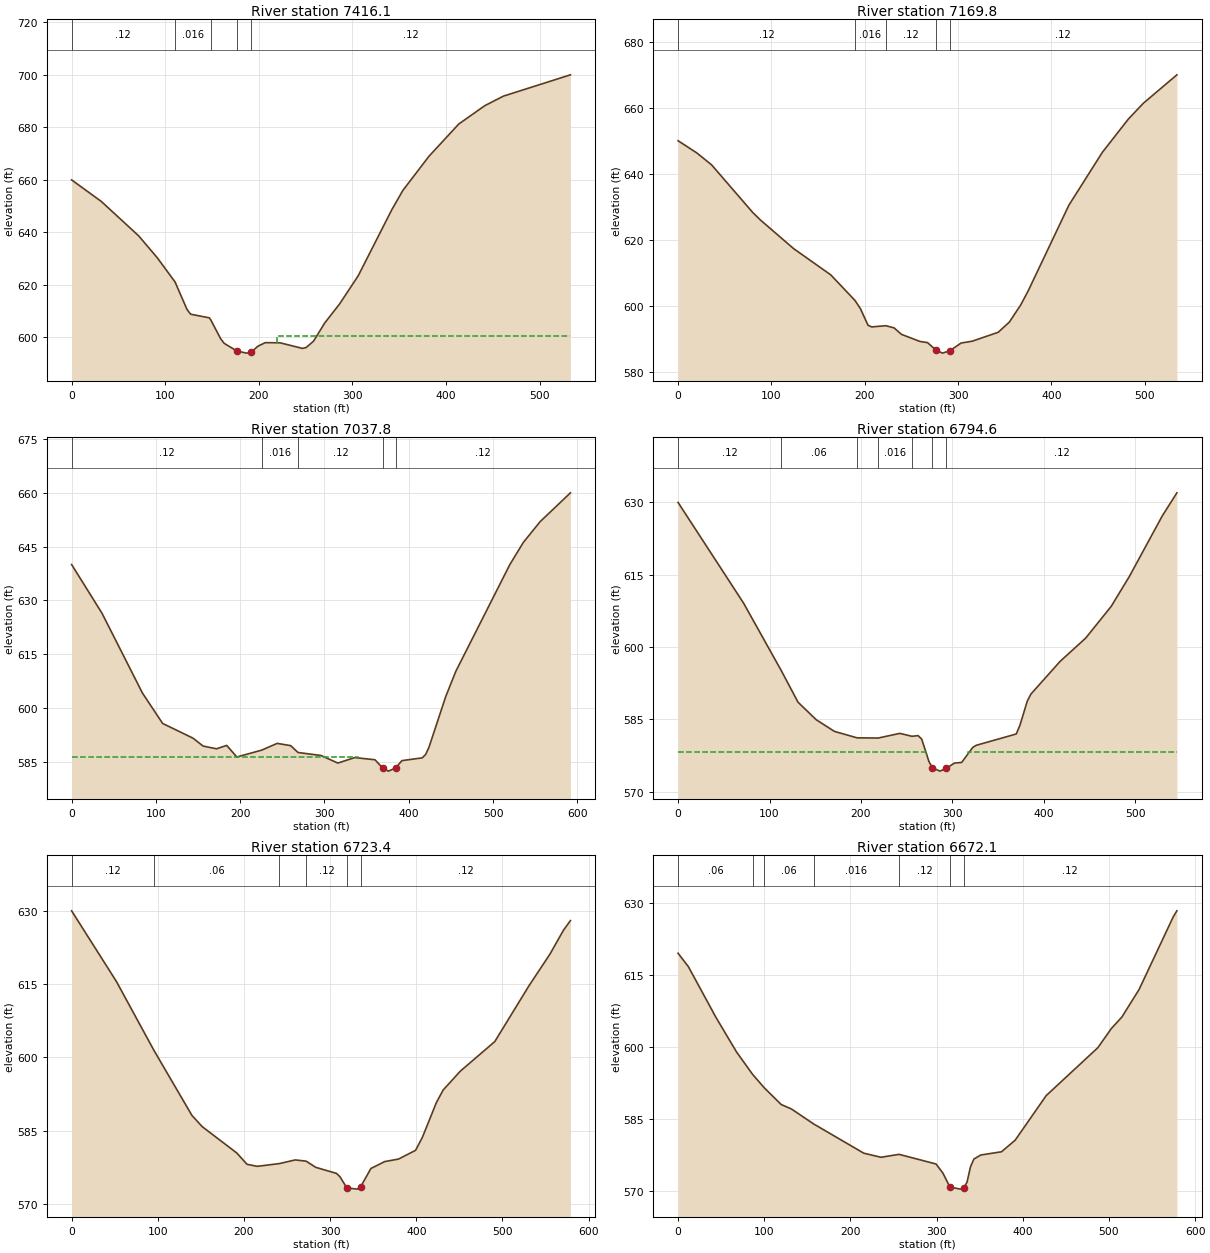
Type RM Length L Ch R = 1 ,7416.1  ,246.8,246.3,246
XS GIS Cut Line= 2
      2347632.75      336947.902     2347650.915      336415.338
#Sta/Elev= 30
       0  659.99    31.8  651.75    71.6  638.68    91.5  630.32  110.49621.1064
   123.3  610.61   127.2   608.8   147.1  607.42  148.58606.6948   159.1  599.54
     163  597.69   176.6  594.78   186.9  593.97   191.6  594.24   198.8  596.56
   206.8  597.96   222.7   597.9   246.6  595.77   250.5  596.09   258.5  598.55
   270.4  605.45   286.3  612.71   306.2  623.46     342  648.57   353.9  655.98
   381.8     669   413.6  681.27   441.4  688.26   461.3   691.9   532.9  700.02
#Mann= 5 ,-1 , 0
       0     .12       0  110.49    .016       0  148.58     .12       0
   176.6    .045       0   191.6     .12       0
#XS Ineff= 2 , 0
                          219.11          600.65
Permanent Ineff=
       F       F
Bank Sta=176.6,191.6
XS Rating Curve= 0 ,0
Exp/Cntr=0.3,0.1

Type RM Length L Ch R = 1 ,7169.8  ,132.4,132,130.6
XS GIS Cut Line= 3
     2347741.104      336923.548      2347885.99      336856.537
     2347868.114      336482.103
#Sta/Elev= 30
       0  650.01      20  646.33    35.9   642.7    79.8  628.32    87.8  626.08
   123.7  617.31   163.6  609.33   189.6601.5623   195.5  599.02   203.5  594.06
   207.5  593.54  222.62593.9083   231.4  593.26   239.4  591.28   259.3  589.12
   267.3  588.78   276.2  586.55   283.3  585.59   291.2   586.3   303.2  588.64
   315.2  589.21   343.1  591.92     355  595.02     367  600.14     375  604.38
   418.8  630.48   454.7  646.52   482.6  656.62   498.6  661.39   534.5     670
#Mann= 5 ,-1 , 0
       0     .12       0   189.6    .016       0  222.62     .12       0
   276.2    .045       0   291.2     .12       0
Bank Sta=276.2,291.2
XS Rating Curve= 0 ,0
Exp/Cntr=0.3,0.1

Type RM Length L Ch R = 1 ,7037.8  ,241.9,243.2,245
XS GIS Cut Line= 2
      2348012.38      337076.272      2348001.02      336484.537
#Sta/Elev= 30
       0     640      36  626.44      84  604.17     108  595.67     144  591.57
     156  589.36     172   588.6     184  589.55     196  586.32  225.37588.2094
   243.9  590.11   259.9  589.48  268.59587.5685   295.9  586.73   315.9  584.62
   335.9  586.15   359.9  585.54   369.3  583.18   375.9  582.37   384.3  583.23
   391.9   585.3   415.9  586.07   419.9  586.97   423.9  588.98   443.9   603.2
   455.9  610.25   519.9  639.98   535.9  646.16   555.8  651.95   591.8     660
#Mann= 5 ,-1 , 0
       0     .12       0  225.37    .016       0  268.59     .12       0
   369.3    .045       0   384.3     .12       0
#XS Ineff= 2 , 0
          339.85   586.3
Permanent Ineff=
       F       F
Bank Sta=369.3,384.3
XS Rating Curve= 0 ,0
Exp/Cntr=0.3,0.1

Type RM Length L Ch R = 1 ,6794.6  ,75,71.2,67.4
XS GIS Cut Line= 3
     2348176.271       337084.38     2348211.275       336716.15
     2348184.114      336542.592
#Sta/Elev= 30
       0     630    71.6  609.12  112.79595.1295   131.2  588.54   151.1   584.9
     171  582.48  195.76 581.142   218.9581.0959   242.6  582.07  255.85581.4584
   262.5   581.6   266.5  580.87   274.4  576.22   278.1  574.93   286.4  574.23
   293.1  574.78   302.3   575.9   310.2  576.04   322.2  579.13   326.1  579.59
   369.9  581.94   373.9  583.73   381.9  588.74   385.9  590.22   417.8     597
   445.8  601.84   473.7  608.42   493.7  614.67   529.6  627.21   545.6     632
#Mann= 7 ,-1 , 0
       0     .12       0  112.79     .06       0  195.76     .12       0
   218.9    .016       0  255.85     .12       0   278.1    .045       0
   293.1     .12       0
#XS Ineff= 2 , 0
          272.24  578.21  317.14          578.22
Permanent Ineff=
       F       F
Bank Sta=278.1,293.1
XS Rating Curve= 0 ,0
Exp/Cntr=0.3,0.1

Type RM Length L Ch R = 1 ,6723.4  ,51.6,51.3,51
XS GIS Cut Line= 3
     2348212.114      337098.949     2348280.491      336894.543
     2348249.005      336532.537
#Sta/Elev= 30
       0     630    51.9  615.56   95.53601.4299   139.7  588.08   151.7  585.78
   191.6  580.42   203.6  578.08   215.5  577.67  241.15578.2319   259.5  578.98
  272.09578.7335   283.4  577.46   307.4  576.22   311.4  575.54   319.4  573.26
   331.3     573   335.3  573.43   347.3  577.22   363.3  578.64   379.3  579.15
   399.2  580.95   407.2  583.65   423.2  590.68   431.2   593.3   451.1  597.16
   491.1  603.22     531  614.71     555   621.1   570.9  626.05   578.9     628
#Mann= 6 ,-1 , 0
       0     .12       0   95.53     .06       0  241.15    .016       0
  272.09     .12       0   319.4    .045       0   335.3     .12       0
Bank Sta=319.4,335.3
XS Rating Curve= 0 ,0
Exp/Cntr=0.3,0.1

Type RM Length L Ch R = 1 ,6672.1  ,62.6,63.7,65.2
XS GIS Cut Line= 3
     2348262.114      337089.227     2348330.491      336884.821
     2348299.005      336522.815
#Sta/Elev= 30
       0  619.51      12  616.71    43.9   606.2    67.8  599.01   86.46594.3416
  100.12591.5316   119.7  588.07   131.7  587.13   157.3  584.04   215.5  577.96
   235.5  577.11  256.48577.7177   299.4  575.71   307.4  573.81   315.4  570.94
   327.4  570.49   331.3  570.71   335.3   571.9   339.3   575.1   343.3  576.74
   351.3  577.58   375.3  578.25   391.2  580.66   427.2  589.92   487.1  599.87
     503   603.9     515  606.24     535  611.97   574.9  627.16   578.9  628.32
#Mann= 7 ,-1 , 0
       0     .06       0   86.46     .08       0  100.12     .06       0
   157.3    .016       0  256.48     .12       0   315.4    .045       0
   331.3     .12       0
Bank Sta=315.4,331.3
XS Rating Curve= 0 ,0
Exp/Cntr=0.3,0.1

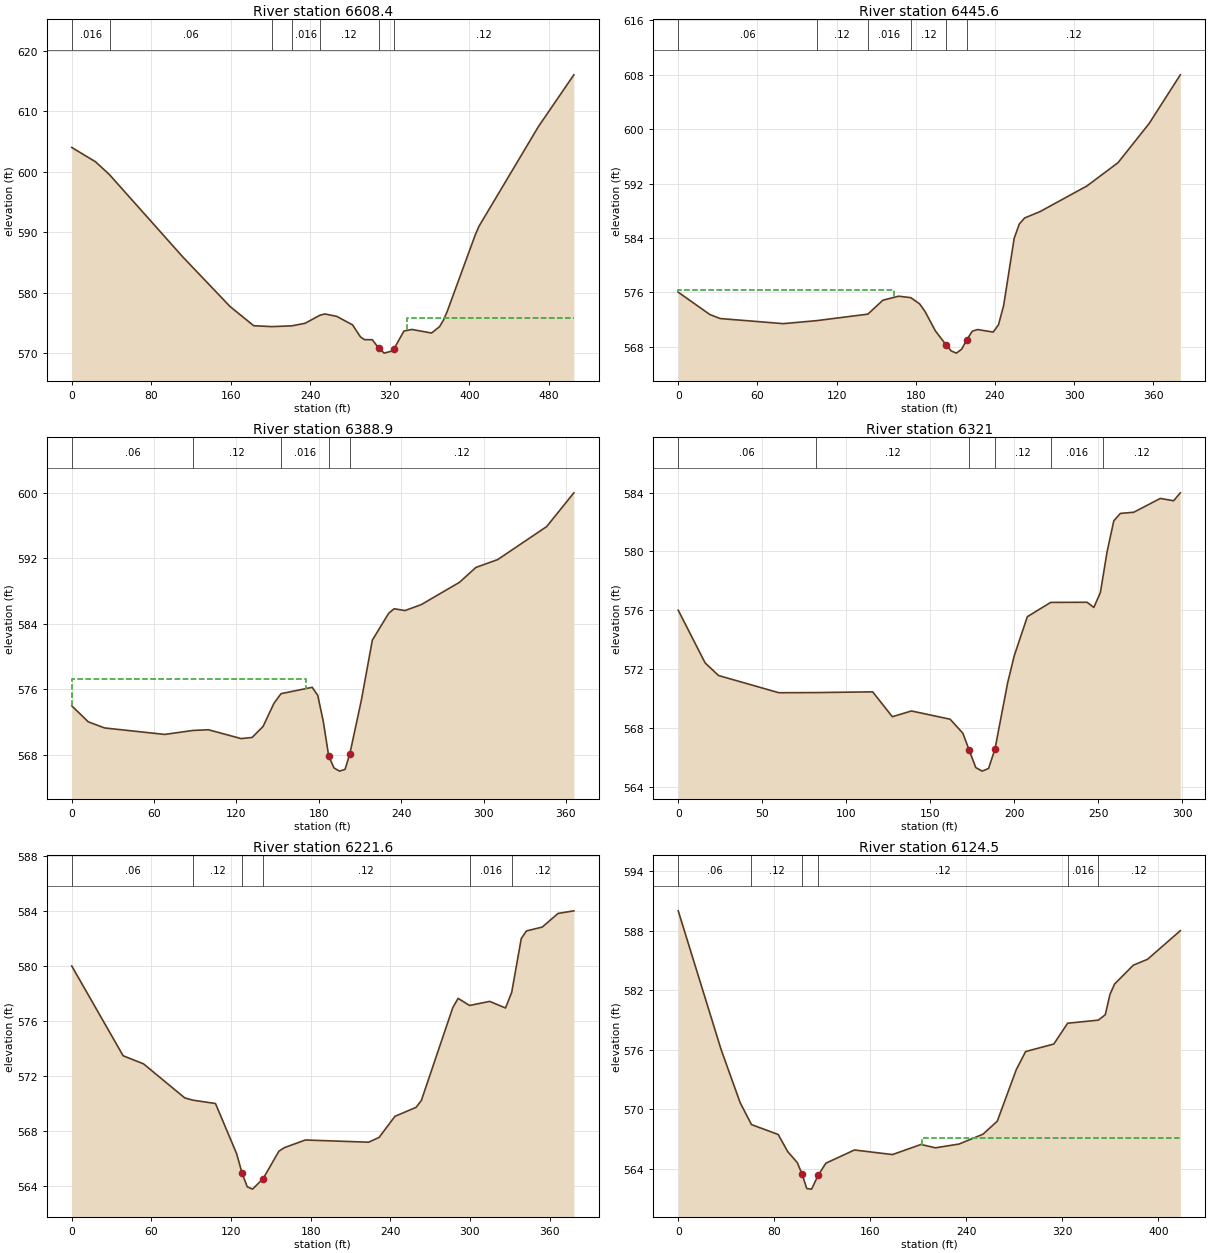
Type RM Length L Ch R = 1 ,6608.4  ,152.4,162.8,172.5
XS GIS Cut Line= 3
     2348337.155      337092.537     2348388.166      336929.189
     2348378.985      336595.408
#Sta/Elev= 30
       0     604    23.9  601.64   37.96599.5066   111.4  585.97   159.2  577.73
     183  574.56  201.25574.4089  221.29574.5338   234.7  574.96  249.61576.2905
   254.6   576.5   266.5   576.1   282.4   574.7   290.4  572.71   294.4  572.26
   302.3  572.24  308.59   570.9   314.2  570.03   322.2  570.38  324.17  570.76
   334.1  573.68   342.1  573.94   361.9  573.35   369.9   574.4   373.9  575.49
   377.8  576.99   405.7   589.5   409.6  590.99   469.3  607.43     505     616
#Mann= 7 ,-1 , 0
       0    .016       0   37.96     .06       0  201.25     .12       0
  221.29    .016       0  249.61     .12       0  308.59    .045       0
  324.17     .12       0
#XS Ineff= 2 , 0
                          337.48          575.81
Permanent Ineff=
       F       F
Bank Sta=308.59,324.17
XS Rating Curve= 0 ,0
Exp/Cntr=0.3,0.1

Type RM Length L Ch R = 1 ,6445.6  ,54.7,56.8,59.2
XS GIS Cut Line= 3
     2348460.905      336999.429     2348560.854      336765.277
     2348557.233      336639.418
#Sta/Elev= 30
       0  576.01    23.9  572.73    31.8  572.13    79.6  571.38  104.89571.8198
  143.72572.7789   155.1  574.83   167.1  575.42  176.28575.2016     183  574.28
     187  573.18   194.9  570.31   202.9  568.28   206.9  567.36   210.8  567.04
   214.8  567.62   218.8  569.04   222.8  570.26   226.8  570.51   238.7  570.14
   242.7  571.21   246.6  574.03   254.6  583.94   258.5  586.05   262.5  586.93
   274.3  587.88   309.7  591.64   333.3  595.07   356.9  600.84   380.5     608
#Mann= 6 ,-1 , 0
       0     .06       0  104.89     .12       0  143.72    .016       0
  176.28     .12       0   202.9    .045       0   218.8     .12       0
#XS Ineff= 2 , 0
          163.71  576.31
Permanent Ineff=
       F       F
Bank Sta=202.9,218.8
XS Rating Curve= 0 ,0
Exp/Cntr=0.3,0.1

Type RM Length L Ch R = 1 ,6388.9  ,52.9,67.9,82.5
XS GIS Cut Line= 3
     2348501.707      336994.945     2348608.765      336803.886
     2348608.114      336657.075
#Sta/Elev= 30
       0     574      12  572.05    23.9   571.3    67.7  570.51   88.29570.9952
    99.6  571.08   123.4     570   131.4  570.14   139.4  571.49   147.3  574.31
  152.48575.4852   175.2  576.26   179.2  575.28   183.2  572.15   187.2  567.88
   191.1  566.41   195.1  566.03   199.1  566.24   202.6  568.15     211   574.7
     219  582.02   230.9   585.3   234.9  585.85   242.8  585.63   254.7  586.36
   282.5  589.08   294.4  590.89   310.3  591.85     346  595.88   365.8     600
#Mann= 5 ,-1 , 0
       0     .06       0   88.29     .12       0  152.48    .016       0
   187.2    .045       0   202.6     .12       0
#XS Ineff= 2 , 0
          170.94  577.29
Permanent Ineff=
       F       F
Bank Sta=187.2,202.6
XS Rating Curve= 0 ,0
Exp/Cntr=0.3,0.1

Type RM Length L Ch R = 1 ,6321    ,100.4,99.4,98.4
XS GIS Cut Line= 4
     2348514.701      337011.217     2348576.254      336908.397
     2348652.423      336872.846     2348657.432      336777.855
#Sta/Elev= 30
       0     576      16  572.42      24  571.56    59.9  570.39   82.05   570.4
   115.8  570.45   127.5  568.76   138.9  569.15   161.9  568.59   169.5  567.64
   173.3  566.48   177.2   565.3     181  565.06   184.8  565.24   188.6  566.55
   196.2  571.08   200.1   572.9   207.9  575.56  221.81576.5306   243.5  576.54
   247.5  576.19   251.4   577.2  252.86578.2147   255.4  579.98   259.4  582.08
   263.3  582.58   271.3  582.66   287.1   583.6     295  583.44     299  583.98
#Mann= 6 ,-1 , 0
       0     .06       0   82.05     .12       0   173.3    .045       0
   188.6     .12       0  221.81    .016       0  252.86     .12       0
Bank Sta=173.3,188.6
XS Rating Curve= 0 ,0
Exp/Cntr=0.3,0.1

Type RM Length L Ch R = 1 ,6221.6  ,113.6,97,80.5
XS GIS Cut Line= 4
     2348592.834      337097.257     2348620.331      336992.537
     2348701.629      336950.229     2348704.805      336771.847
#Sta/Elev= 30
       0  579.99    38.7  573.47    54.1  572.88    85.1  570.41   91.27570.2435
   108.3     570   124.2  566.36   128.2  564.98   132.2  563.95   136.2  563.78
   144.1  564.53   156.1  566.54   160.1  566.79     176  567.35   223.7  567.19
   231.6  567.54   243.5  569.07   259.4  569.72   263.4  570.22   287.1  576.97
   291.1  577.64  299.73577.1245   314.9  577.42   326.8  576.94  331.45578.0634
   338.7  581.99   342.6  582.54   354.5  582.82   366.4  583.81   378.3     584
#Mann= 6 ,-1 , 0
       0     .06       0   91.27     .12       0   128.2    .045       0
   144.1     .12       0  299.73    .016       0  331.45     .12       0
Bank Sta=128.2,144.1
XS Rating Curve= 0 ,0
Exp/Cntr=0.3,0.1

Type RM Length L Ch R = 1 ,6124.5  ,123.6,113.7,103.8
XS GIS Cut Line= 3
      2348676.13      337140.553     2348778.486      336878.165
     2348774.045       336741.59
#Sta/Elev= 30
       0     590    35.7  576.04    51.6  570.68   61.01568.4786    83.3  567.48
    91.2  565.76    99.2  564.65   103.1  563.51   107.1  562.04   111.1  561.98
  116.65  563.39     123  564.59   146.8  565.92   178.5  565.46   202.3  566.48
   214.2  566.14     234  566.52   253.9  567.51   265.8  568.82   281.6     574
   289.4  575.83   312.9  576.59  324.44578.6838     350578.9936   355.8  579.54
   359.7  581.59   363.6  582.64   379.2  584.53     391  585.12   418.3     588
#Mann= 6 ,-1 , 0
       0     .06       0   61.01     .12       0   103.1    .045       0
  116.65     .12       0  324.44    .016       0     350     .12       0
#XS Ineff= 2 , 0
                          202.94          567.09
Permanent Ineff=
       F       F
Bank Sta=103.1,116.65
XS Rating Curve= 0 ,0
Exp/Cntr=0.3,0.1

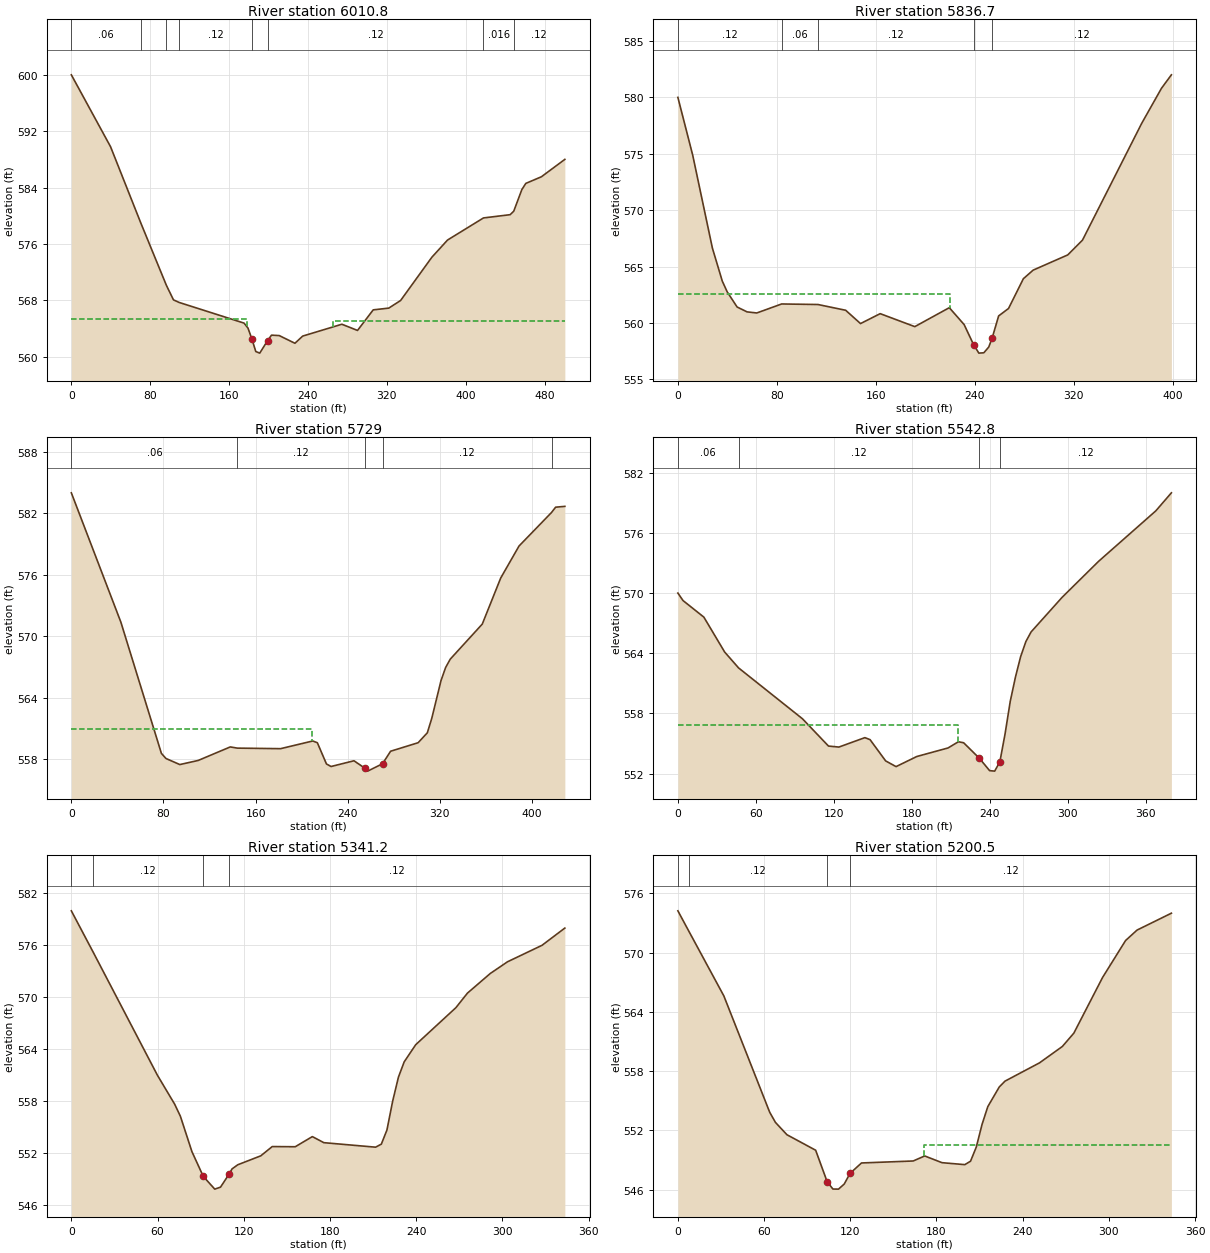
Type RM Length L Ch R = 1 ,6010.8  ,182,174.1,166
XS GIS Cut Line= 3
     2348730.231      337206.654     2348827.209      337095.632
     2348802.812      336743.235
#Sta/Elev= 30
       0     600    39.8  589.79   70.35579.0095   96.41570.1249   103.6  568.06
  109.42 567.691   175.2  564.76   179.2  564.05   183.1  562.52   187.1  560.73
   191.1   560.5     199  562.26     203  563.05   210.9  562.99   226.8   561.9
   234.7  562.92   274.4   564.6   290.3  563.72   306.2  566.64     322  566.89
     334  567.97   365.7  574.11   381.6  576.55  418.07579.6888   445.1  580.15
  448.76580.6441     457  583.72     461  584.59   476.8  585.53   500.6     588
#Mann= 8 ,-1 , 0
       0     .06       0   70.35     .12       0   96.41     .06       0
  109.42     .12       0   183.1    .045       0     199     .12       0
  418.07    .016       0  448.76     .12       0
#XS Ineff= 2 , 0
          177.87  565.39  265.02          565.09
Permanent Ineff=
       F       F
Bank Sta=183.1,199
XS Rating Curve= 0 ,0
Exp/Cntr=0.3,0.1

Type RM Length L Ch R = 1 ,5836.7  ,106.7,107.7,108.7
XS GIS Cut Line= 2
     2349052.114      337176.616     2348885.543      336813.966
#Sta/Elev= 30
       0     580      12  574.87    27.9  566.64    35.9  563.71    39.9  562.75
    47.9  561.41    55.9  560.98    63.8  560.88   83.91561.6794  113.27561.6314
   135.7  561.12   147.7  559.94   163.6  560.82   191.6  559.67   219.5  561.35
   231.5  559.85   239.1  558.08   243.4  557.32   247.4  557.35   251.4  557.86
   254.1  558.64   259.4  560.62   267.4  561.28   279.4  563.92   287.3  564.68
   315.3  566.03   327.2  567.34   375.1   577.7   391.1  580.81   399.1     582
#Mann= 5 ,-1 , 0
       0     .12       0   83.91     .06       0  113.27     .12       0
   239.1    .045       0   254.1     .12       0
#XS Ineff= 2 , 0
          220.01  562.54
Permanent Ineff=
       F       F
Bank Sta=239.1,254.1
XS Rating Curve= 0 ,0
Exp/Cntr=0.3,0.1

Type RM Length L Ch R = 1 ,5729    ,177.5,186.2,195
XS GIS Cut Line= 3
     2349113.375      337160.537     2349119.499      337086.516
     2348986.264      336758.345
#Sta/Elev= 30
       0     584      43  571.39    78.2  558.59    82.2  558.09    94.2   557.5
   110.1   557.9     138  559.22  144.09559.1036   181.7  559.05   209.6   559.8
   213.6  559.63   221.5  557.56   225.5  557.31   245.4  557.87   255.2  557.12
   257.3  556.86   270.2  557.58   277.2   558.8   301.1  559.63   309.1   560.6
     313  562.03     321   565.7     325  566.97     329  567.78   356.8   571.2
   372.8  575.69   388.7  578.81  416.96582.0867   420.5   582.6   428.5  582.68
#Mann= 5 ,-1 , 0
       0     .06       0  144.09     .12       0   255.2    .045       0
   270.2     .12       0  416.96    .016       0
#XS Ineff= 2 , 0
          208.88  560.92
Permanent Ineff=
       F       F
Bank Sta=255.2,270.2
XS Rating Curve= 0 ,0
Exp/Cntr=0.3,0.1

Type RM Length L Ch R = 1 ,5542.8  ,201.4,201.5,201.5
XS GIS Cut Line= 2
     2349224.114      337130.362     2349213.924      336750.728
#Sta/Elev= 30
       0     570       4  569.25      20   567.6      36  564.12   46.69562.5372
    95.9  557.46   115.9  554.74   123.9  554.64   143.9  555.58   147.9  555.38
   159.9  553.26   167.9  552.69   183.9   553.7   207.9  554.55   215.9  555.17
   219.9  555.07   231.9  553.54   239.9  552.29   243.8  552.24   247.8  553.17
   251.8  555.96   255.8  559.21   259.8  561.63   263.8  563.67   267.8  565.16
   271.8  566.12   295.8  569.59   323.8  573.17   367.8   578.2   379.8     580
#Mann= 4 ,-1 , 0
       0     .06       0   46.69     .12       0   231.9    .045       0
   247.8     .12       0
#XS Ineff= 2 , 0
          215.72  556.86
Permanent Ineff=
       F       F
Bank Sta=231.9,247.8
XS Rating Curve= 0 ,0
Exp/Cntr=0.3,0.1

Type RM Length L Ch R = 1 ,5341.2  ,139.7,140.7,141.8
XS GIS Cut Line= 2
     2349348.709      337107.942     2349342.834      336764.537
#Sta/Elev= 30
       0  579.99   15.18 575.226    59.9  561.02    71.9  557.68    75.9  556.28
    83.9  552.21    91.8  549.35    99.8  547.88   103.8  548.11   109.8  549.62
   111.8  550.21   115.8  550.69   131.8  551.72   139.8  552.79   155.8  552.77
   167.7  553.94   175.7  553.24   211.7  552.72   215.7  553.07   219.6   554.7
   223.6  558.04   227.6   560.8   231.6  562.56   239.6  564.54   267.6  568.82
   275.6  570.49   291.5  572.76   303.5  574.11   327.5  576.01   343.4     578
#Mann= 4 ,-1 , 0
       0     .06       0   15.18     .12       0    91.8    .045       0
   109.8     .12       0
Bank Sta=91.8,109.8
XS Rating Curve= 0 ,0
Exp/Cntr=0.3,0.1

Type RM Length L Ch R = 1 ,5200.5  ,153,154.6,152.8
XS GIS Cut Line= 2
     2349484.521      337127.153     2349492.114      336783.698
#Sta/Elev= 30
       0  574.24    7.79572.1331      32  565.62    63.9  553.84    67.9  552.81
    75.9  551.56    95.9  549.99   103.9   546.8   107.9  546.06   111.8  546.05
   115.8  546.57   119.8  547.64   127.8   548.7   163.8   548.9   171.8  549.41
   183.8  548.73   199.7  548.53   203.7  548.88   207.7  550.31   211.7   552.6
   215.7   554.4   223.7   556.4   227.7  556.99   251.7  558.84   267.6   560.5
   275.6  561.85   295.6  567.49   311.6  571.23   319.6  572.29   343.5     574
#Mann= 4 ,-1 , 0
       0     .06       0    7.79     .12       0   103.9    .045       0
   119.8     .12       0
#XS Ineff= 2 , 0
                          171.54          550.47
Permanent Ineff=
       F       F
Bank Sta=103.9,119.8
XS Rating Curve= 0 ,0
Exp/Cntr=0.3,0.1

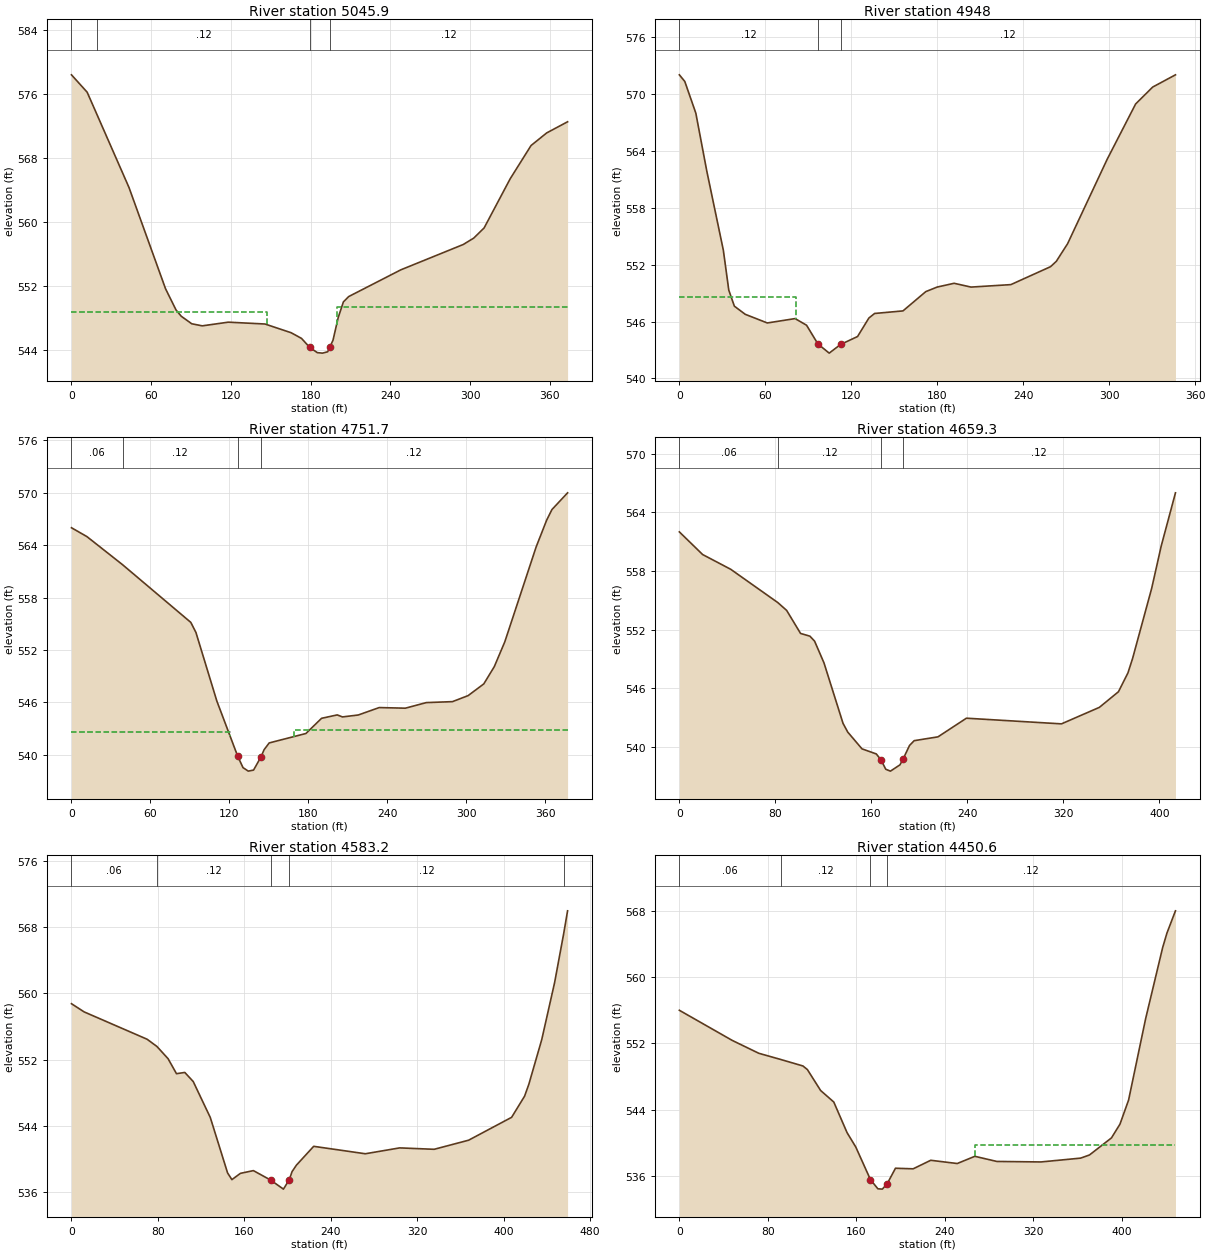
Type RM Length L Ch R = 1 ,5045.9  ,100.8,97.9,97.9
XS GIS Cut Line= 3
     2349606.312      337146.117     2349622.593      336942.142
     2349583.001      336778.201
#Sta/Elev= 30
       0  578.41    11.8  576.24   19.37 573.377    43.3  564.32    70.8  551.66
    78.7  549.01    82.6  548.23    90.5  547.29    98.4  547.03     118  547.49
   145.6  547.26   165.3  546.17   173.1  545.46   179.3  544.33     185  543.68
   188.9  543.62   192.8  543.79   194.3  544.33   196.8  545.24   200.7  548.06
   204.6  550.02   208.6  550.69   247.8  554.03   294.8   557.2   302.7     558
   310.5  559.27   330.1  565.41   345.8  569.57   357.6  571.15   373.3  572.54
#Mann= 4 ,-1 , 0
       0     .06       0   19.37     .12       0   179.3    .045       0
   194.3     .12       0
#XS Ineff= 2 , 0
          147.31  548.82  199.44          549.44
Permanent Ineff=
       F       F
Bank Sta=179.3,194.3
XS Rating Curve= 0 ,0
Exp/Cntr=0.3,0.1

Type RM Length L Ch R = 1 ,4948    ,208.4,196.3,182.6
XS GIS Cut Line= 3
     2349744.114      337092.184      2349716.35      337024.773
      2349687.73      336752.921
#Sta/Elev= 30
       0     572     3.8   571.3    11.5  567.96    19.2  561.82    30.7  553.52
    34.5  549.31    38.4  547.62      46  546.76    61.4  545.85    80.8  546.31
    88.8  545.61    96.7  543.64   104.6  542.67   112.5  543.58   124.4  544.42
   132.3  546.37   136.3  546.85   156.1  547.12     172  549.15   179.9  549.63
   191.8  550.03   203.6  549.63   231.4  549.89   259.1  551.78   263.1  552.34
     271   554.2   298.7  563.12   318.5  568.93   330.4  570.71   346.3     572
#Mann= 3 ,-1 , 0
       0     .12       0    96.7    .045       0   112.5     .12       0
#XS Ineff= 2 , 0
           81.32  548.62
Permanent Ineff=
       F       F
Bank Sta=96.7,112.5
XS Rating Curve= 0 ,0
Exp/Cntr=0.3,0.1

Type RM Length L Ch R = 1 ,4751.7  ,92.5,92.4,92.3
XS GIS Cut Line= 3
     2349901.862      337070.285      2349903.71      336975.678
     2349756.114      336734.822
#Sta/Elev= 30
       0     566    11.8  564.98    38.8561.7708    90.7  555.16    94.6  554.01
   110.5  546.15   126.4  539.81   130.4  538.52   134.4  538.12   138.4  538.24
   144.1  539.76   146.4  540.57   150.3  541.35   178.2  542.43   190.1  544.17
     202  544.56     206  544.33     218  544.55   233.9   545.4   253.8  545.33
   269.7  545.97   289.6  546.08   301.5  546.77   313.4  548.11   321.4  550.09
   329.4  552.94   353.2   563.8   361.2  566.87   365.2  568.08   377.1     570
#Mann= 4 ,-1 , 0
       0     .06       0    38.8     .12       0   126.4    .045       0
   144.1     .12       0
#XS Ineff= 2 , 0
          120.42   542.6  169.31          542.82
Permanent Ineff=
       F       F
Bank Sta=126.4,144.1
XS Rating Curve= 0 ,0
Exp/Cntr=0.3,0.1

Type RM Length L Ch R = 1 ,4659.3  ,76.9,76.1,75.3
XS GIS Cut Line= 3
     2349984.514      337052.138      2349986.75      336935.574
     2349830.715      336683.138
#Sta/Elev= 30
       0     562    19.4  559.68    42.8  558.17   82.02554.7623    89.4  553.96
     101   551.6   108.8  551.32   112.7  550.81   120.5  548.59   136.4  542.39
   140.3   541.5   152.2  539.78   164.1  539.26     168  538.66     172  537.69
   175.9   537.5   183.8  538.14  186.46  538.74   191.8  540.13   195.7  540.62
   215.5  541.01   239.2  542.92   318.4  542.34     350  544.03   365.9  545.63
   373.8  547.56   377.7  549.05   393.6  556.23   401.5  560.54   413.4     566
#Mann= 4 ,-1 , 0
       0     .06       0   82.02     .12       0     168    .045       0
  186.46     .12       0
Bank Sta=168,186.46
XS Rating Curve= 0 ,0
Exp/Cntr=0.3,0.1

Type RM Length L Ch R = 1 ,4583.2  ,132.7,132.6,132.4
XS GIS Cut Line= 3
     2350057.367      337026.508     2350059.603      336909.944
     2349876.114      336620.608
#Sta/Elev= 30
       0  558.76    11.7  557.77      70  554.46   79.07553.5879    89.4  552.11
    97.2  550.29   104.9  550.44   112.7  549.34   128.5  544.99   144.5  538.28
   148.5  537.47   156.4  538.23   168.4  538.56   184.3  537.42   196.2  536.32
  201.51  537.44   204.2  538.44   208.2  539.22   224.2   541.5     272   540.6
   303.8  541.31   335.7  541.14   367.6  542.24   407.4  545.01   419.4  547.57
   423.3  548.99   435.3  554.42   447.2  561.32  455.63567.2689   459.2     570
#Mann= 5 ,-1 , 0
       0     .06       0   79.07     .12       0   184.3    .045       0
  201.51     .12       0  455.63    .016       0
Bank Sta=184.3,201.51
XS Rating Curve= 0 ,0
Exp/Cntr=0.3,0.1

Type RM Length L Ch R = 1 ,4450.6  ,204.5,214.9,225.1
XS GIS Cut Line= 4
     2350159.182      336988.537     2350178.003      336870.242
     2350027.816      336644.517     2350017.042      336587.609
#Sta/Elev= 30
       0     556    47.9  552.36    71.9  550.81   91.62550.0672   111.8  549.28
   115.8  548.85   127.8  546.32   139.7  544.93   151.7  541.24   159.6   539.5
   172.9  535.56   179.6  534.46   183.6  534.42   187.9  535.04   195.5  536.94
   211.5  536.87   227.4   537.9   251.4  537.51   267.3  538.38   287.2  537.76
   327.1   537.7     363  538.16     371  538.54   390.9   540.6   398.6  542.26
   406.4  545.17   421.8  554.98   437.2  563.56   441.1  565.32   448.8     568
#Mann= 4 ,-1 , 0
       0     .06       0   91.62     .12       0   172.9    .045       0
   187.9     .12       0
#XS Ineff= 2 , 0
                          267.67           539.7
Permanent Ineff=
       F       F
Bank Sta=172.9,187.9
XS Rating Curve= 0 ,0
Exp/Cntr=0.3,0.1

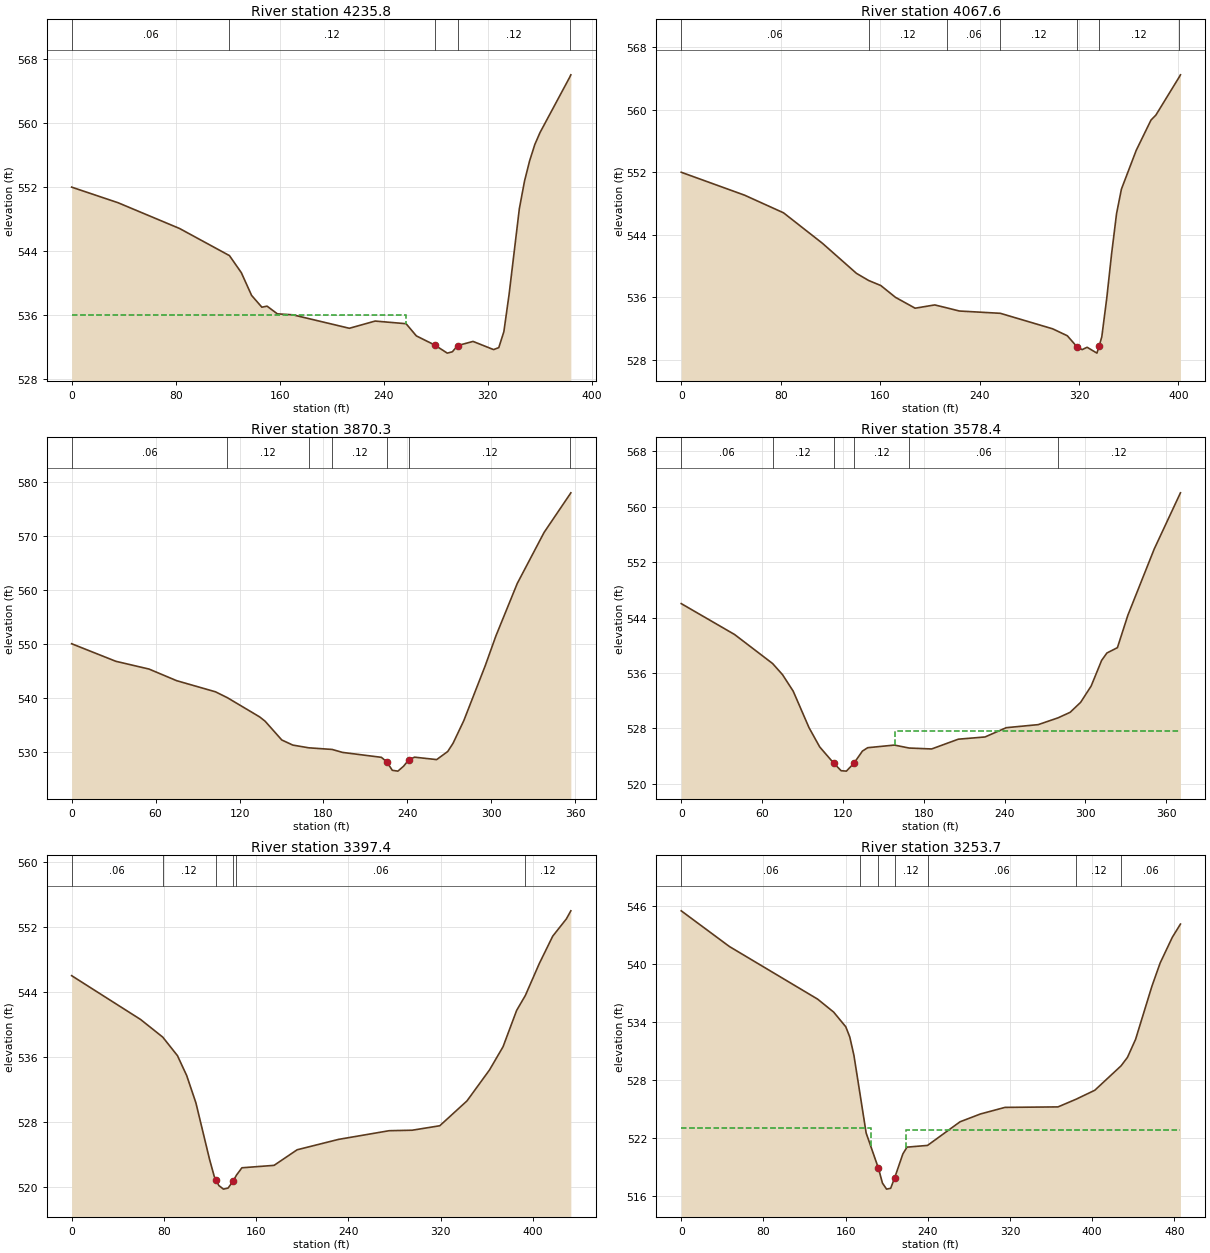
Type RM Length L Ch R = 1 ,4235.8  ,155.4,168.1,180.9
XS GIS Cut Line= 3
     2350265.051      336931.601     2350307.694      336804.117
     2350260.114      336559.213
#Sta/Elev= 30
       0  551.99    35.6  550.05      83  546.83  121.37 543.446   130.5  541.32
   138.4  538.48   146.3  537.01   150.3  537.14   158.2  536.18   170.1  536.06
   213.6  534.38   233.4  535.28   257.2  534.95   265.1  533.43   279.1   532.3
   288.9  531.28   292.8  531.45   296.8  532.22   308.7  532.74   324.5  531.72
   328.5  531.97   332.4  533.96   336.4  538.59   344.3   549.3   348.3  552.76
   352.2  555.27   356.2  557.31   360.2   558.8  382.94 565.675   383.9     566
#Mann= 5 ,-1 , 0
       0     .06       0  121.37     .12       0   279.1    .045       0
   296.8     .12       0  382.94    .016       0
#XS Ineff= 2 , 0
          256.87     536
Permanent Ineff=
       F       F
Bank Sta=279.1,296.8
XS Rating Curve= 0 ,0
Exp/Cntr=0.3,0.1

Type RM Length L Ch R = 1 ,4067.6  ,202.4,197.4,192.3
XS GIS Cut Line= 3
     2350332.114      336938.612     2350374.225      336771.448
     2350470.036      336563.148
#Sta/Elev= 30
       0     552    50.9  549.07    82.3  546.81   113.6  542.91     141  539.06
   150.8538.1476   160.6   537.5   172.4  535.99   188.2   534.6     204  535.02
  213.95534.6324   223.8  534.24  256.75533.9467   298.9  531.96   310.7  531.07
   318.6  529.63   322.6   529.3   326.6   529.6   334.5  528.85  336.36  529.81
   338.4  530.93   342.4  535.88   346.3  541.57   350.3  546.72   354.2  549.84
   366.1   554.8     378  558.68   381.9  559.31  400.78564.2078   401.7  564.47
#Mann= 7 ,-1 , 0
       0     .06       0   150.8     .12       0  213.95     .06       0
  256.75     .12       0   318.6    .045       0  336.36     .12       0
  400.78    .016       0
Bank Sta=318.6,336.36
XS Rating Curve= 0 ,0
Exp/Cntr=0.3,0.1

Type RM Length L Ch R = 1 ,3870.3  ,297.8,291.9,284.9
XS GIS Cut Line= 3
     2350572.519      336932.537     2350628.114      336669.571
     2350614.236      336582.658
#Sta/Elev= 30
       0     550    31.6  546.74    55.3   545.3    75.1  543.14   102.8  541.08
  111.33539.9847   134.4  536.42   138.3  535.62   150.2  532.14   158.1  531.19
  169.44530.6882   186.2530.3823   193.7  529.83   221.4  528.92   225.3  528.06
   229.2  526.51   233.2  526.36   237.2  527.26   241.1  528.49   245.1  528.95
   260.9   528.5   268.8     530   272.6  531.52   280.3  535.73   295.6  545.91
   303.2  551.42   318.5  561.18   337.7  570.66  356.36577.8228   356.8     578
#Mann= 7 ,-1 , 0
       0     .06       0  111.33     .12       0  169.44     .06       0
   186.2     .12       0   225.3    .045       0   241.1     .12       0
  356.36    .016       0
Bank Sta=225.3,241.1
XS Rating Curve= 0 ,0
Exp/Cntr=0.3,0.1

Type RM Length L Ch R = 1 ,3578.4  ,188.1,181,173.9
XS GIS Cut Line= 3
     2350852.996      336911.655     2350849.971       336626.88
     2350796.114      336560.076
#Sta/Elev= 30
       0  546.01    39.6  541.55   67.83537.3603    75.2  535.75    83.1  533.38
    94.9  528.09   102.8  525.32   113.2  522.98   118.7  521.89   122.6  521.83
   128.2  522.97   134.5  524.72   138.4  525.21   158.2  525.59  169.17525.1633
   185.9  525.03   205.7  526.44   225.5  526.76   241.3   528.1     265  528.54
  279.78529.5241   288.7  530.32   296.5  531.76   304.3  534.11   312.1  537.82
     316  538.88   323.8  539.65   331.6  544.35   351.1  553.88   370.6     562
#Mann= 6 ,-1 , 0
       0     .06       0   67.83     .12       0   113.2    .045       0
   128.2     .12       0  169.17     .06       0  279.78     .12       0
#XS Ineff= 2 , 0
                          158.96          527.69
Permanent Ineff=
       F       F
Bank Sta=113.2,128.2
XS Rating Curve= 0 ,0
Exp/Cntr=0.3,0.1

Type RM Length L Ch R = 1 ,3397.4  ,148.2,143.8,139.1
XS GIS Cut Line= 3
     2351072.831       336907.82     2350972.372      336600.537
     2350912.295      336508.718
#Sta/Elev= 30
       0     546    59.9  540.59   79.04 538.424    91.8  536.14    99.8  533.69
   107.8  530.32   119.7  523.32   123.7  521.26   125.1  520.86   127.7  520.13
   131.7  519.69   135.7  519.82   140.1  520.68  142.96521.4109   147.7  522.32
   175.6  522.62   195.6  524.54   231.5  525.82   275.4  526.89   295.4  526.95
   319.3   527.5   342.9  530.56   362.5  534.39   374.2  537.24     386  541.72
  393.57543.5651   405.6  547.48   417.3  550.87   429.1  552.99     433  553.99
#Mann= 6 ,-1 , 0
       0     .06       0   79.04     .12       0   125.1    .045       0
   140.1     .12       0  142.96     .06       0  393.57     .12       0
Bank Sta=125.1,140.1
XS Rating Curve= 0 ,0
Exp/Cntr=0.3,0.1

Type RM Length L Ch R = 1 ,3253.7  ,88,88,88.1
XS GIS Cut Line= 3
     2351171.717      336909.267     2351173.363      336749.119
     2351013.424       336465.18
#Sta/Elev= 30
       0  545.45    46.9  541.76   132.8  536.32   148.4  534.98   160.2  533.46
   164.1   532.4   168.1  530.52  173.91526.6155     180  522.49     192  518.83
   195.9   517.3   199.9  516.68   203.9  516.77   207.8  517.86   215.8  520.33
   219.8  521.02  239.78 521.199   271.4  523.64   291.3  524.45   315.2  525.13
   366.8  525.18  384.43525.9752   402.6   526.9  428.17529.4235   434.4   530.3
   442.3  532.16   458.2  537.65   466.2  540.05   478.1  542.72     486  544.08
#Mann= 7 ,-1 , 0
       0     .06       0  173.91     .12       0     192    .045       0
   207.8     .12       0  239.78     .06       0  384.43     .12       0
  428.17     .06       0
#XS Ineff= 2 , 0
          184.76  522.96   219.1          522.76
Permanent Ineff=
       F       F
Bank Sta=192,207.8
XS Rating Curve= 0 ,0
Exp/Cntr=0.3,0.1