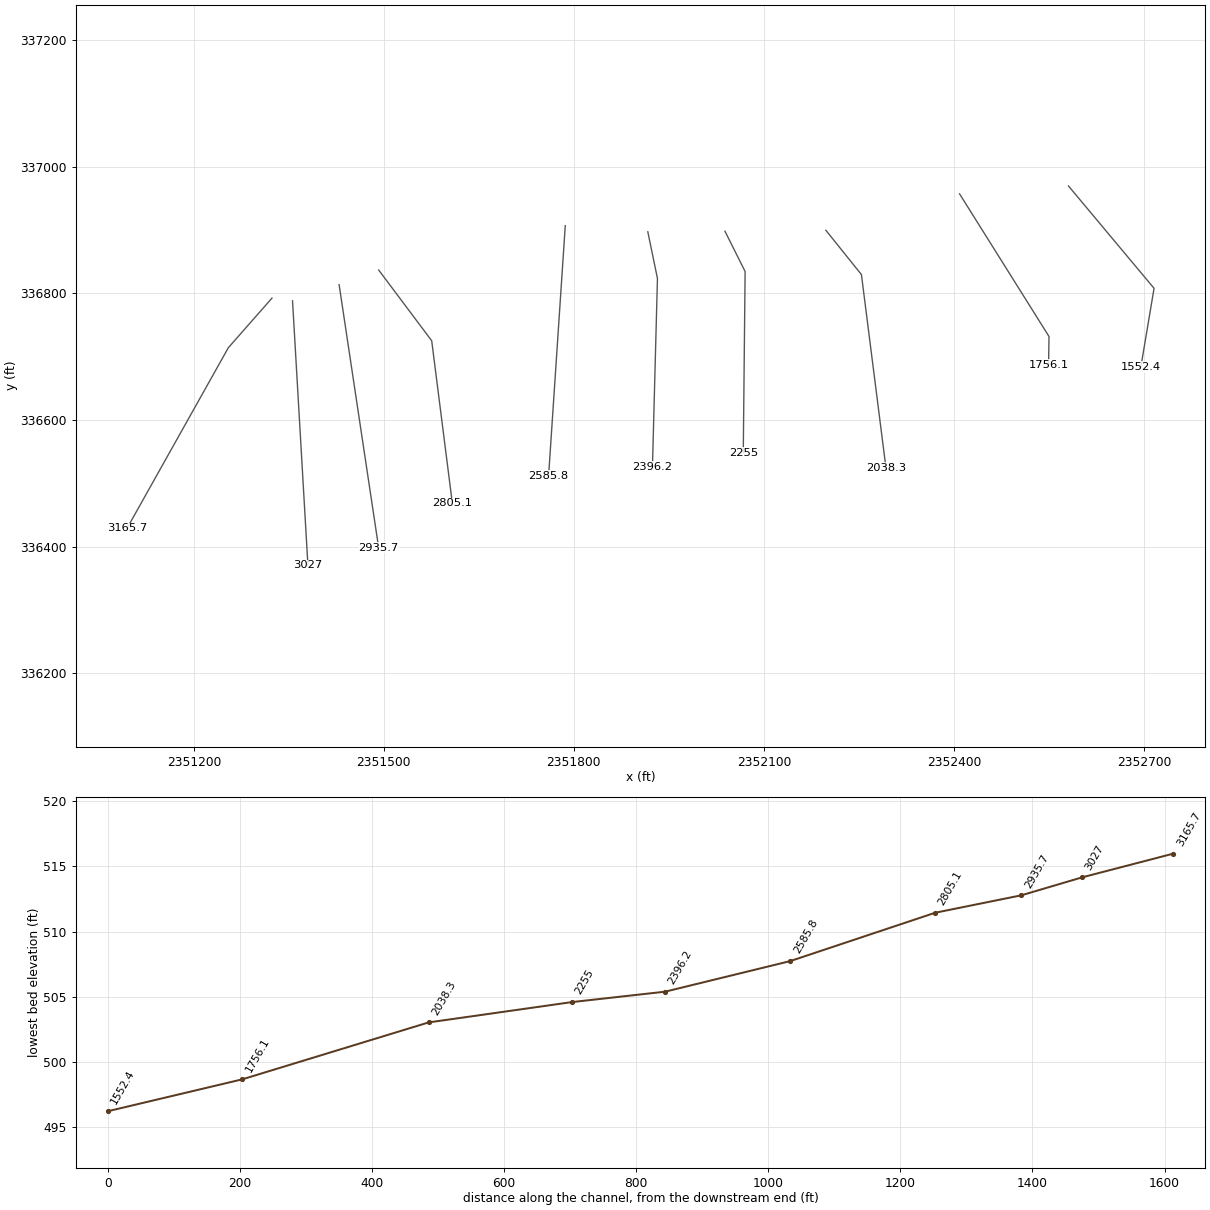
HEC-RAS study TUBRUN.prj: TUBRUN

--- TUBRUN.g01 (geometry) --- (continued)

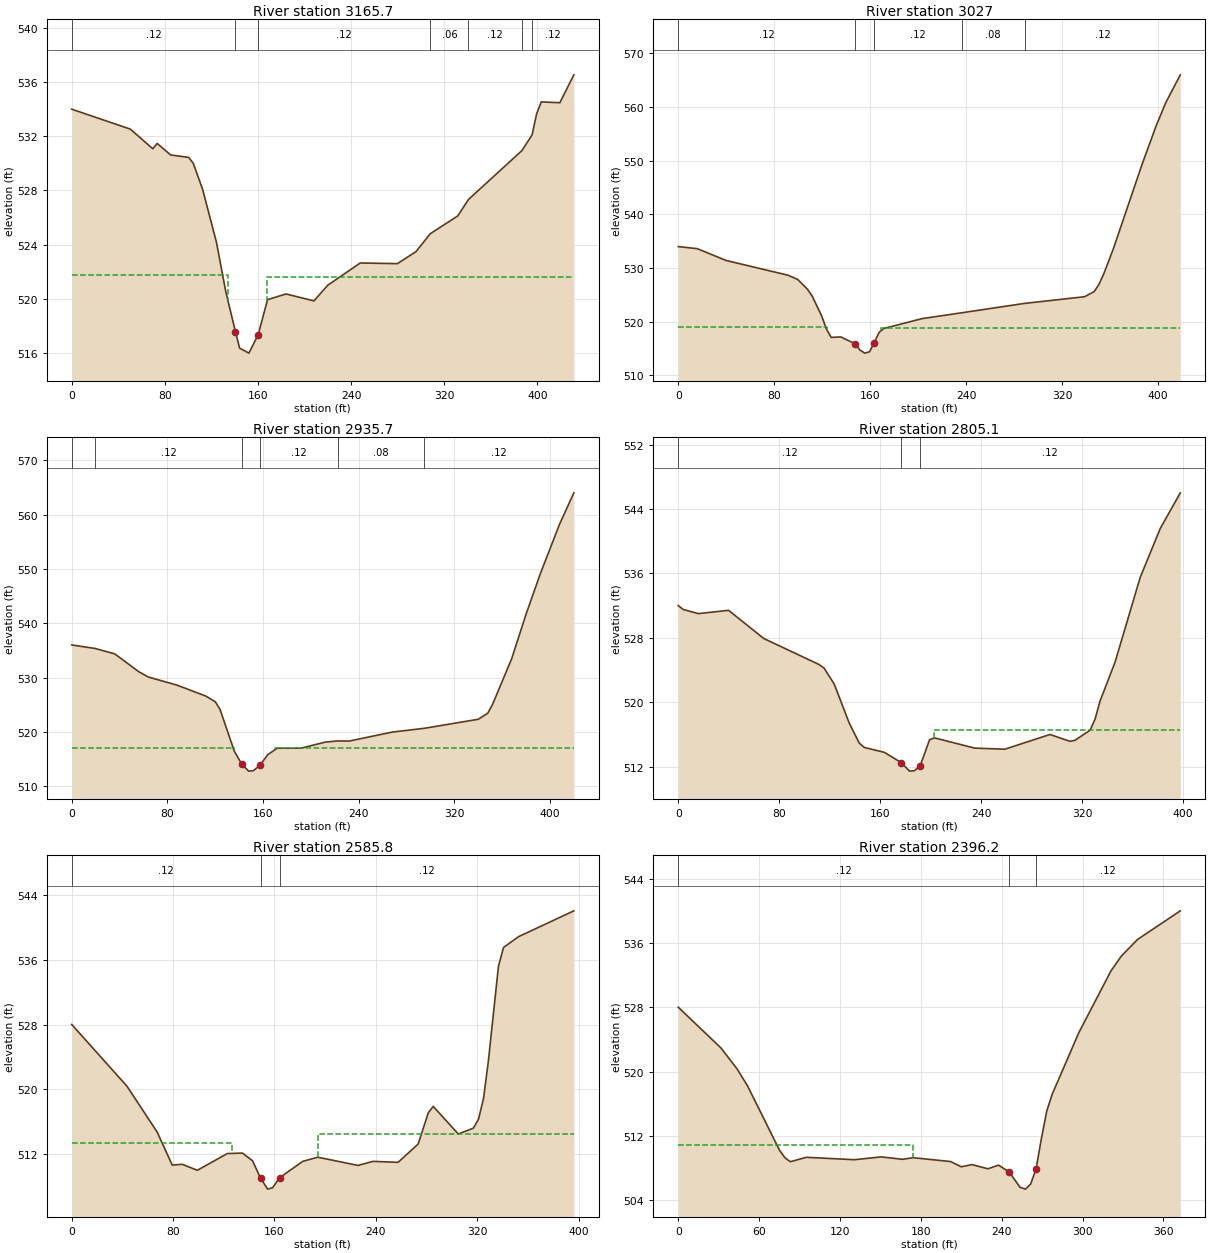
Type RM Length L Ch R = 1 ,3165.7  ,125.7,138.7,151.4
XS GIS Cut Line= 3
     2351323.335      336792.433     2351254.418       336714.04
     2351094.492      336428.841
#Sta/Elev= 30
       0     534    50.3  532.53    69.6  531.08    73.4  531.47      85  530.62
   100.5  530.44   104.4     530   112.4  528.09   124.3  524.18   132.3  520.54
   140.6  517.57   144.2  516.35   152.2  515.98   160.2  517.35   168.2  519.93
   184.1  520.35   208.1  519.84     220     521   247.9  522.64   279.8  522.59
   295.8  523.48  307.97524.7969   331.7  526.12  340.84527.3292  386.75530.9406
  395.48532.0964   399.5  533.68   403.4  534.54   419.4  534.48   431.4  536.54
#Mann= 7 ,-1 , 0
       0     .12       0   140.6    .045       0   160.2     .12       0
  307.97     .06       0  340.84     .12       0  386.75     .06       0
  395.48     .12       0
#XS Ineff= 2 , 0
          134.53  521.75  167.56          521.61
Permanent Ineff=
       F       F
Bank Sta=140.6,160.2
XS Rating Curve= 0 ,0
Exp/Cntr=0.3,0.1

Type RM Length L Ch R = 1 ,3027    ,89.2,91.4,93.5
XS GIS Cut Line= 2
     2351355.811      336788.233     2351380.114      336370.554
#Sta/Elev= 30
       0     534    15.9  533.61    39.8  531.42    91.6  528.66    99.6  527.87
   107.6  526.08   111.6  524.78   119.5   521.1   123.5  518.64   127.5  517.08
   135.5  517.17   147.4  515.88   151.4  514.72   155.4  514.15   159.4   514.4
   163.4  516.11   167.4  518.01   171.3  518.74   203.2  520.58  236.52521.6761
  288.59523.4134   338.7  524.66   346.7  525.63   350.6  526.96   354.6  528.92
   362.6  533.59   386.5   549.3   398.5  556.64   406.4  560.87   418.4     566
#Mann= 5 ,-1 , 0
       0     .12       0   147.4    .045       0   163.4     .12       0
  236.52     .08       0  288.59     .12       0
#XS Ineff= 2 , 0
          124.23  518.97  169.31          518.91
Permanent Ineff=
       F       F
Bank Sta=147.4,163.4
XS Rating Curve= 0 ,0
Exp/Cntr=0.3,0.1

Type RM Length L Ch R = 1 ,2935.7  ,131.1,130.6,130.1
XS GIS Cut Line= 2
     2351429.379      336813.642     2351491.795      336398.307
#Sta/Elev= 30
       0     536   19.63 535.353      36  534.35      56  531.09      64   530.1
      88  528.61     112  526.61     120  525.56     124  524.16     136  516.44
  142.21  514.05     148  512.78     152  512.87  157.75  513.94     164  515.82
     172     517     192  517.01     212  518.12  222.69518.3364     232  518.31
     268  519.96  295.05520.6673     340  522.32     348  523.44     352  525.06
     368  533.47     380  541.64     392  549.13     408   558.2     420     564
#Mann= 6 ,-1 , 0
       0     .06       0   19.63     .12       0  142.21    .045       0
  157.75     .12       0  222.69     .08       0  295.05     .12       0
#XS Ineff= 2 , 0
          135.49  517.03  170.28          517.07
Permanent Ineff=
       F       F
Bank Sta=142.21,157.75
XS Rating Curve= 0 ,0
Exp/Cntr=0.3,0.1

Type RM Length L Ch R = 1 ,2805.1  ,223.6,219.3,215
XS GIS Cut Line= 3
     2351491.901       336836.75     2351575.563      336725.088
     2351608.114       336468.74
#Sta/Elev= 30
       0     532       4  531.51      16     531    39.9  531.41    67.8  527.91
   111.6  524.68   115.6  524.23   123.6  522.26   135.5  517.42   143.5  514.91
   147.5  514.38   163.4  513.77   176.8  512.49   183.3  511.44   187.2  511.49
   191.8  512.13   199.2  515.34   203.1  515.57   234.9   514.3   258.8  514.16
   294.6  515.99   310.5  515.14   314.4  515.27   326.4  516.52   330.4  517.93
   334.3  520.14   346.2  524.98   366.1  535.49     382  541.57   397.9     546
#Mann= 3 ,-1 , 0
       0     .12       0   176.8    .045       0   191.8     .12       0
#XS Ineff= 2 , 0
                          202.37           516.5
Permanent Ineff=
       F       F
Bank Sta=176.8,191.8
XS Rating Curve= 0 ,0
Exp/Cntr=0.3,0.1

Type RM Length L Ch R = 1 ,2585.8  ,188.5,189.6,190.3
XS GIS Cut Line= 2
      2351786.46      336906.883     2351760.114      336511.483
#Sta/Elev= 30
       0     528    43.6   520.4    67.4  514.76    79.3  510.69    87.2  510.79
    99.1  510.05   122.8  512.11   134.7  512.17   142.7  511.22     149  509.09
   154.6  507.73   158.5   507.9     164  509.12   182.3  511.15   194.2  511.66
   225.9  510.65   237.8  511.15   257.6  511.03   273.4  513.28   281.4  517.12
   285.3  517.92   305.1  514.52     317  515.24     321  516.32     325  518.88
   328.9  523.59   336.8  535.18   340.8  537.49   352.7  538.82   396.3     542
#Mann= 3 ,-1 , 0
       0     .12       0     149    .045       0     164     .12       0
#XS Ineff= 2 , 0
          126.17   513.4  194.23          514.55
Permanent Ineff=
       F       F
Bank Sta=149,164
XS Rating Curve= 0 ,0
Exp/Cntr=0.3,0.1

Type RM Length L Ch R = 1 ,2396.2  ,140.8,141.2,141.6
XS GIS Cut Line= 3
     2351916.779      336897.202     2351932.005      336823.508
     2351924.114      336526.377
#Sta/Elev= 30
       0  528.01    31.7  522.94    43.6  520.35    51.5   518.2    75.2   510.2
    79.2  509.28    83.2  508.79    95.1  509.34   130.7  509.04   150.6  509.39
   166.4  509.09   174.3  509.29   202.1  508.81     210  508.16   217.9  508.43
   229.8  507.91   237.7  508.37   245.7  507.48   253.6  505.61   257.6  505.38
   261.5  506.02   265.5  507.91   269.4  511.64   273.4  515.08   277.4  517.16
   297.2  524.84     321  532.51   328.9   534.4   340.8  536.44   372.5     540
#Mann= 3 ,-1 , 0
       0     .12       0   245.7    .045       0   265.5     .12       0
#XS Ineff= 2 , 0
          174.11  510.82
Permanent Ineff=
       F       F
Bank Sta=245.7,265.5
XS Rating Curve= 0 ,0
Exp/Cntr=0.3,0.1

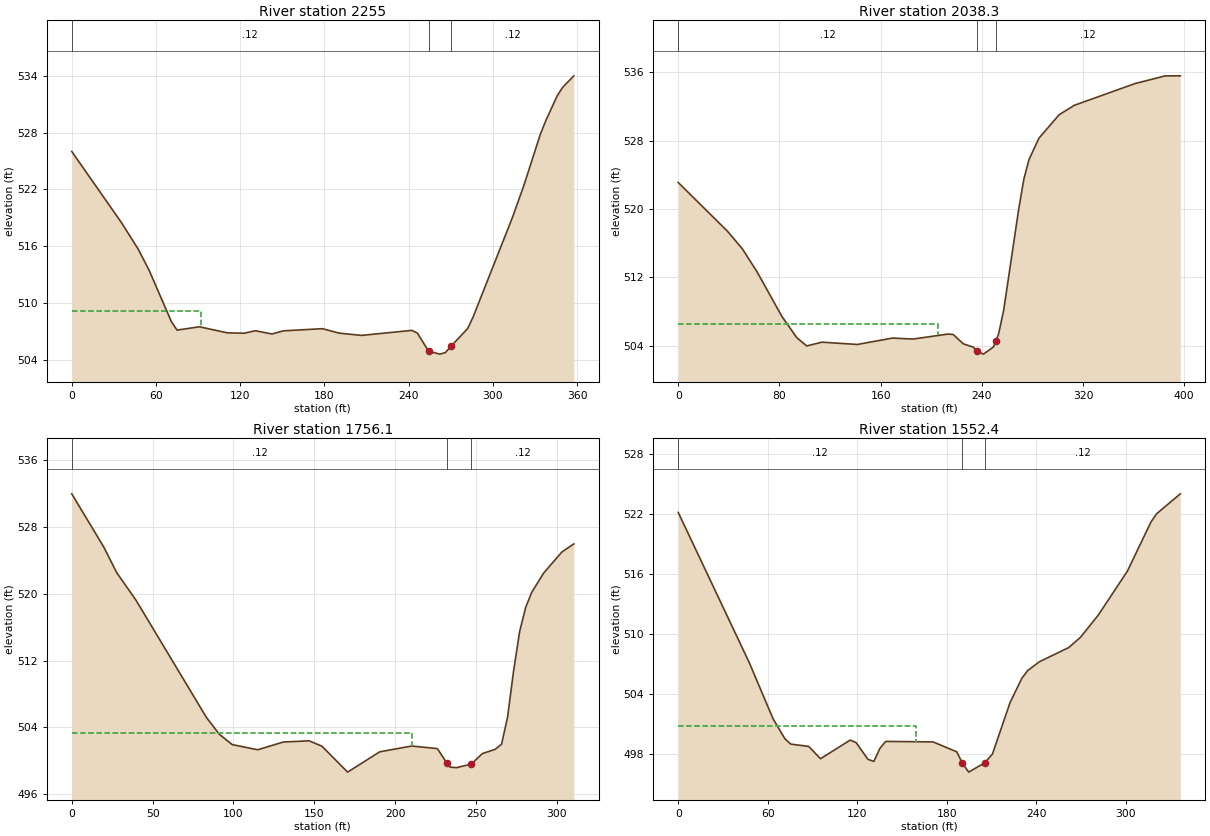
Type RM Length L Ch R = 1 ,2255    ,213.6,216.7,219.8
XS GIS Cut Line= 3
     2352038.638      336898.014     2352070.413      336834.497
     2352067.499      336547.921
#Sta/Elev= 30
       0     526    35.5  518.46    47.4  515.66    55.2  513.41      71     508
      75  507.12    90.9  507.47   110.8  506.83   122.8  506.79   130.7  507.05
   142.7  506.71   150.6  507.04   178.5  507.27   190.4   506.8   206.4  506.56
   242.2  507.09   246.2   506.8   254.1   504.9   262.1  504.58   266.1  504.74
   270.1  505.41     282  507.29     286  508.56   313.8     519   321.8  522.32
   333.7   527.8   337.7  529.29   345.7  531.87   349.6  532.78   357.6     534
#Mann= 3 ,-1 , 0
       0     .12       0   254.1    .045       0   270.1     .12       0
#XS Ineff= 2 , 0
           92.26  509.19
Permanent Ineff=
       F       F
Bank Sta=254.1,270.1
XS Rating Curve= 0 ,0
Exp/Cntr=0.3,0.1

Type RM Length L Ch R = 1 ,2038.3  ,272.4,282.2,291.9
XS GIS Cut Line= 3
      2352197.92      336899.565     2352254.053      336829.635
     2352292.734      336524.751
#Sta/Elev= 30
       0   523.1      39  517.39    50.7  515.34    62.4  512.63    81.9  507.45
    93.7  504.95   101.6  503.98   113.6  504.42   141.6  504.15   169.5   504.9
   185.5  504.78   213.4  505.37   217.4  505.32   225.4  504.23   233.4  503.83
     236  503.38   241.3  503.02   249.3  503.86     251   504.5   253.3  505.37
   257.3  508.12   269.3  520.06   273.3   523.5   277.3  525.76   285.2  528.28
   301.2  531.03   313.2  532.13   361.1  534.67     385  535.57     397  535.58
#Mann= 3 ,-1 , 0
       0     .12       0     236    .045       0     251     .12       0
#XS Ineff= 2 , 0
          205.77  506.55
Permanent Ineff=
       F       F
Bank Sta=236,251
XS Rating Curve= 0 ,0
Exp/Cntr=0.3,0.1

Type RM Length L Ch R = 1 ,1756.1  ,200.3,203.7,195
XS GIS Cut Line= 3
     2352409.061      336957.035     2352550.235      336731.849
     2352549.534      336687.117
#Sta/Elev= 30
       0     532    19.8  525.62    27.8  522.55    39.7  519.26    83.3   505.2
    91.2   503.2    99.2  501.95     115  501.33   130.9  502.26   146.8   502.4
   154.7  501.76   170.6  498.65   190.4  501.08   210.2  501.78   226.1  501.47
   232.1   499.7     234  499.25     238  499.19   247.1  499.61   253.9  500.87
   261.8  501.38   265.8     502   269.5  505.23   273.2  510.72     277  515.52
   280.7  518.38   284.4  520.18   291.9  522.52   303.1  525.03   310.5     526
#Mann= 3 ,-1 , 0
       0     .12       0   232.1    .045       0   247.1     .12       0
#XS Ineff= 2 , 0
          210.12  503.35
Permanent Ineff=
       F       F
Bank Sta=232.1,247.1
XS Rating Curve= 0 ,0
Exp/Cntr=0.3,0.1

Type RM Length L Ch R = 1 ,1552.4  ,1599.2,1552.4,1533.9
XS GIS Cut Line= 3
     2352580.964      336969.544     2352716.114      336807.911
     2352695.244      336683.667
#Sta/Elev= 30
       0  522.15    47.7  507.12    63.6  501.53    71.6  499.52    75.5     499
    87.5  498.77    95.4  497.54   115.3   499.4   119.3  499.15   127.2  497.48
   131.2  497.27   135.2  498.56   139.1  499.27   170.9  499.22   186.8  498.23
   190.5  497.11   194.8   496.2   205.5  497.13   210.7     498   222.5  503.14
   230.4  505.57   234.3  506.34   242.2  507.23   261.9  508.65   269.8  509.68
   281.6  511.87   301.2  516.28     317  521.19   320.9  522.03   336.7  524.01
#Mann= 3 ,-1 , 0
       0     .12       0   190.5    .045       0   205.5     .12       0
#XS Ineff= 2 , 0
          159.27  500.77
Permanent Ineff=
       F       F
Bank Sta=190.5,205.5
XS Rating Curve= 0 ,0
Exp/Cntr=0.3,0.1

Chan Stop Cuts=-1
Use User Specified Reach Order=0
Composite Channel Slope=5